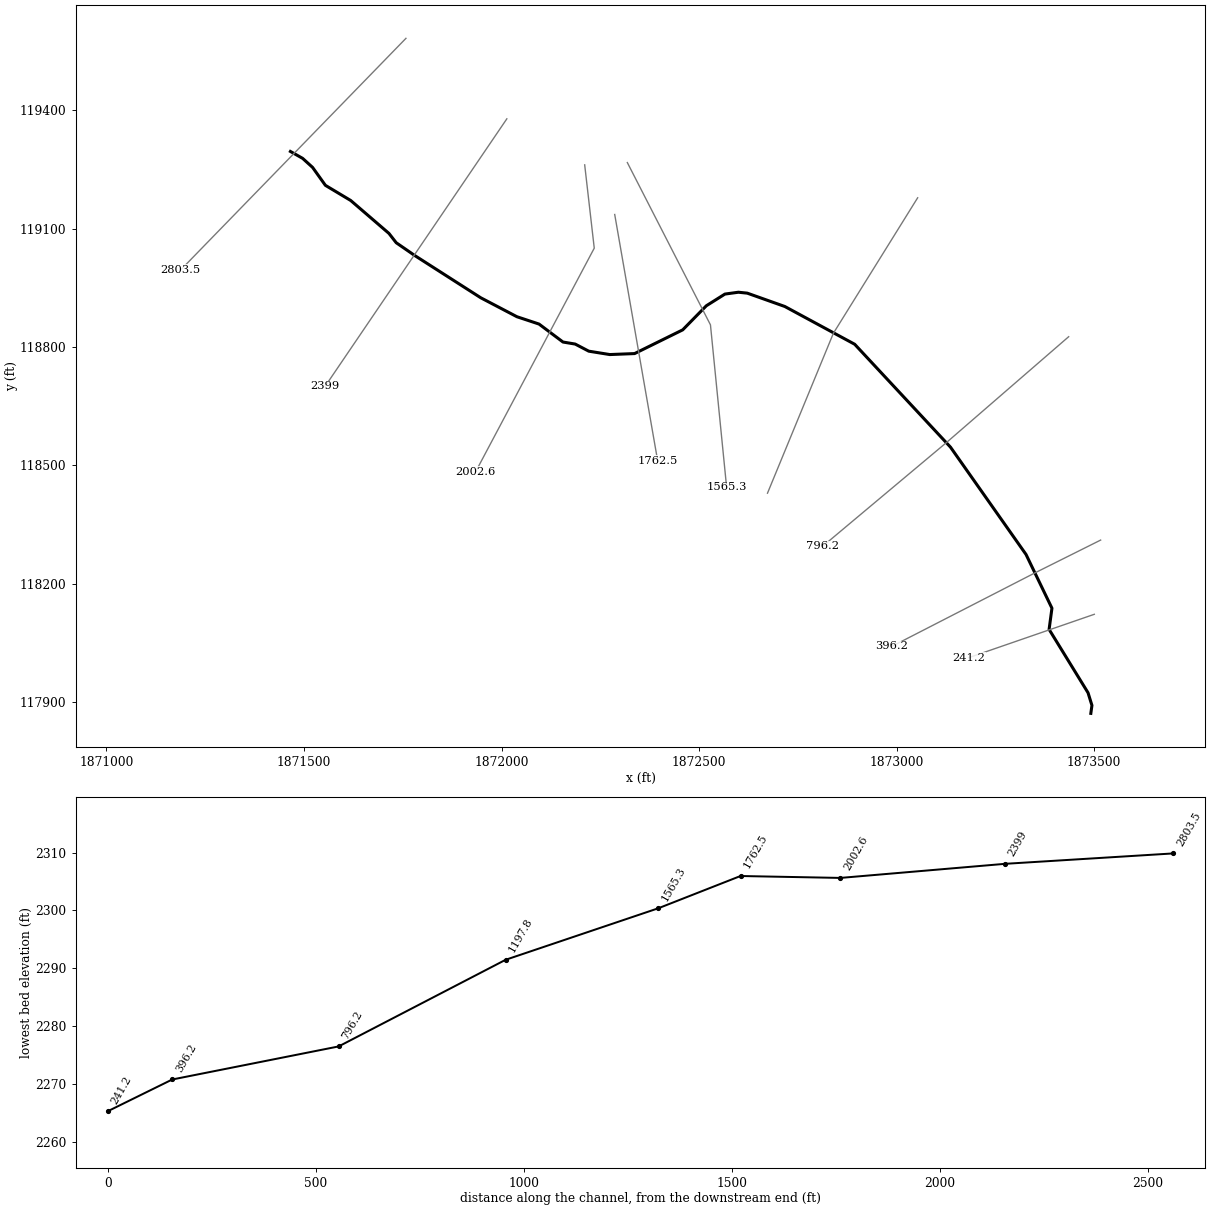
--- MllCrk.prj (project) ---

Proj Title=MllCrk
Current Plan=p01
Default Exp/Contr=0,0
English Units
Geom File=g01
Flow File=f01
Plan File=p01
BEGIN DESCRIPTION:
END DESCRIPTION:
DSS Export Rating Curves= 0
DSS Export Rating Curve Sorted= 0
DSS Export Volume Flow Curves= 0
DXF OffsetX= 0
DXF OffsetY= 0
DXF ScaleX= 0
DXF ScaleY= 0

--- MllCrk.p01 (plan) ---

Plan Title=Floodplain
Program Version=4.00
Geom File=g01
Flow File=f01
K Sum by GR=0
Std Step Tol=0.01
Critical Tol=0.01
Num of Std Step Trials=20
Max Error Tol=0.3
Flow Tol Ratio=0.001
Split Flow NTrial=30
Split Flow Tol=0.02
Split Flow Ratio=0.02
Log Output Level=0
Friction Slope Method=1
Unsteady Friction Slope Method=2
Unsteady Bridges Friction Slope Method=1
Global Log Level=0
CheckData=False
Run HTab=0
Run UNet=0
Run PostProcess=0
UNET Theta=0
UNET Theta Warmup=0
UNET ZTol=0
UNET ZSATol=0
UNET MxIter=0
UNET MaxInSteps=0
UNET DtIC=0
UNET DtMin=0
UNET MaxCRTS=0
UNET WFStab=0
UNET SFStab=0
UNET WFX=0
UNET SFX=0
UNET DSS MLevel=0
UNET DZMax Abort=0
UNET Convert EG Bridges=0
UNET Use Existing IB Tables=0
UNET Froude Limit=0
UNET Froude Power=0
Write IC File=0
Echo Input=False
Echo Output=False
Write Detailed=0

--- MllCrk.f01 (steady flow) ---

Flow Title=NFF Regression Equation
Program Version=4.00
Number of Profiles=1
Profile Names=P100yr
River Rch & RM=MllCrk,Main      ,2803.5
498.4059
River Rch & RM=MllCrk,Main      ,241.2
535.6406
Boundary for River Rch & Prof#=MllCrk,Main      ,1
Up Type=0
Dn Type=3
Dn Slope=0.029605

--- MllCrk.g01 (geometry) ---

Geom Title=USGS 3m DEM
Program Version=4.10

River Reach=MllCrk          ,Main
Reach XY= 30
     1871465.632      119295.994     1871496.534      119278.459
     1871521.709      119255.574     1871554.173      119210.056
      1871618.25      119171.611     1871714.964      119088.182
       1871733.4      119064.479      1871781.46      119031.295
     1871947.381      118924.877     1872038.923      118876.817
      1872094.81      118858.238     1872155.449      118812.642
     1872186.344      118807.493     1872220.673       118789.47
     1872273.882      118780.888     1872336.658      118783.381
     1872458.445      118843.526     1872518.305      118904.673
     1872565.292      118934.281     1872599.392      118938.962
     1872621.882      118936.619     1872716.934      118902.765
       1872893.7      118807.016     1873136.205      118545.994
      1873327.36      118273.863      1873392.93       118137.59
      1873385.74      118083.831     1873484.261      117923.157
     1873494.152      117891.151     1873491.347      117870.867

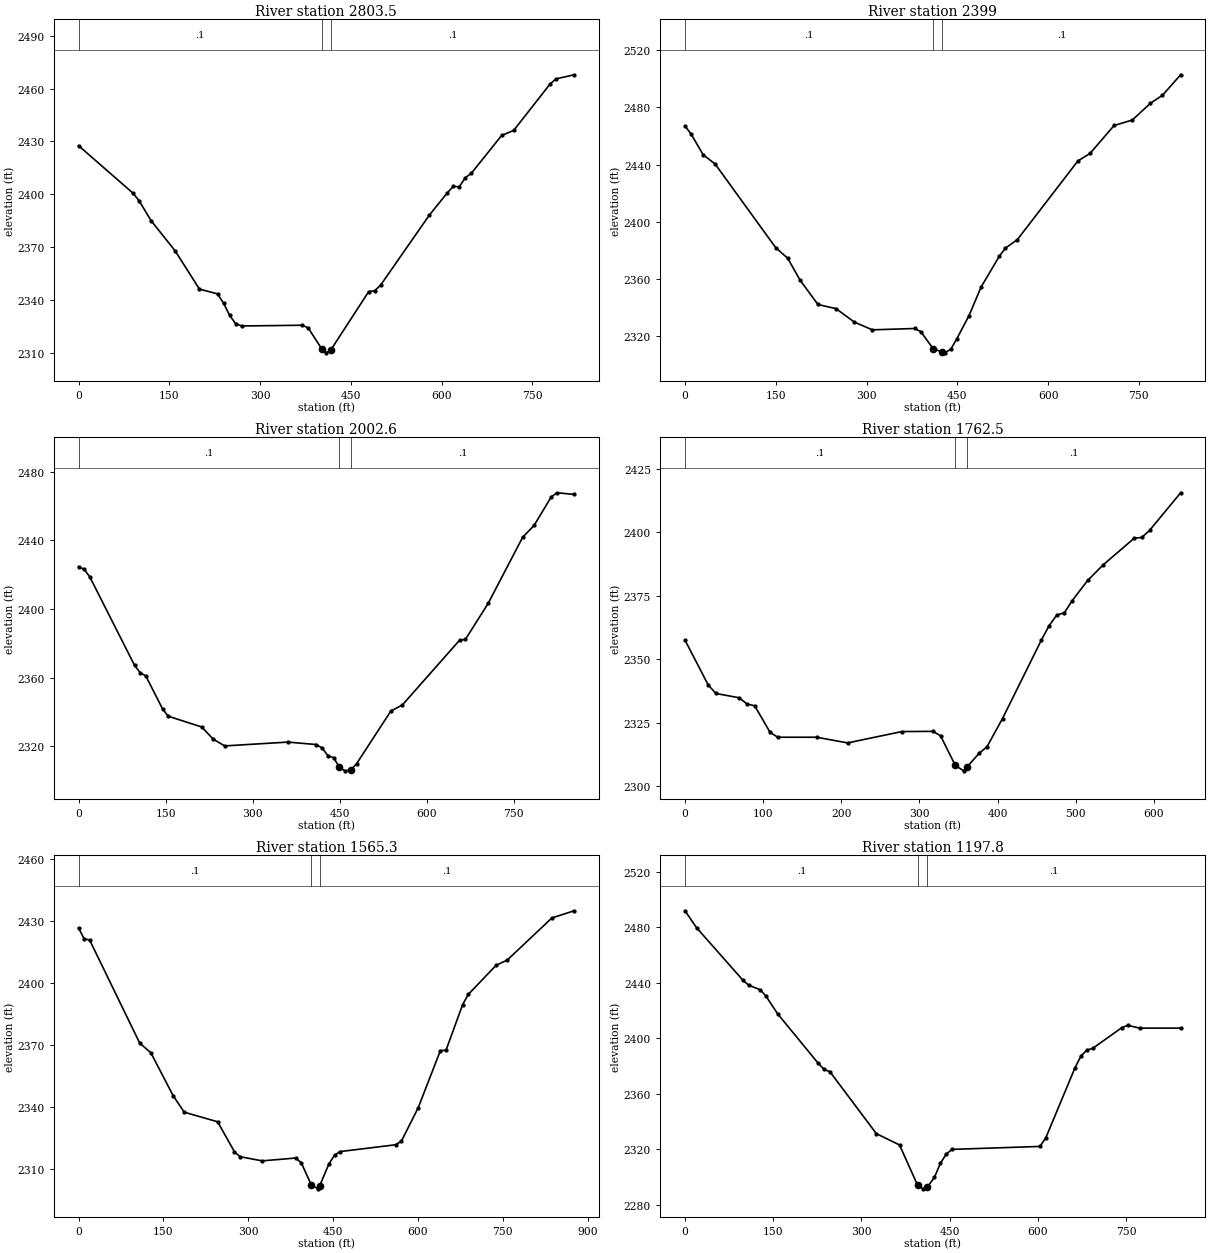
Type RM Length L Ch R = 1 ,2803.5  ,400.3,404.4,408.5
XS GIS Cut Line= 3
     1871758.014      119582.879     1871472.807      119289.029
     1871187.601       118995.18
#Sta/Elev= 30
       0 2427.57    89.9  2400.6    99.9 2396.37   119.8 2385.01   159.8 2367.73
   199.8 2346.06   229.7 2343.37   239.7 2338.06   249.7 2331.16   259.7 2326.41
   269.7 2325.12   369.6 2325.54   379.5 2324.06     402 2312.05   409.5 2309.86
     417 2311.55   479.4 2344.59   489.4 2345.14   499.4 2348.42   579.3 2387.92
   609.3 2400.71   619.2 2404.41   629.2  2404.2   639.2 2409.37   649.2 2411.91
   699.2 2433.35   719.1 2436.22     779  2462.5     789 2465.49     819 2467.82
#Mann= 3 , 0 , 0
       0      .1       0     402    .045       0     417      .1       0
Bank Sta=402,417
XS Rating Curve= 0 ,0
Exp/Cntr=0.3,0.1

Type RM Length L Ch R = 1 ,2399    ,393.8,396.3,398.7
XS GIS Cut Line= 3
     1872013.352      119378.742     1871783.581       119039.78
      1871553.81      118700.817
#Sta/Elev= 30
       0 2467.05      10 2461.47      30  2446.9    49.9 2440.34   149.8 2381.84
   169.8 2374.34   189.8 2359.23   219.7 2341.95   249.7    2339   279.7 2329.64
   309.6 2324.18   379.5 2325.12   389.5 2322.97   410.2 2310.93   425.2 2308.63
   429.5 2308.06   439.5 2310.75   449.4  2318.1   469.4 2334.22   489.4 2354.28
   519.4 2375.75   529.4 2381.41   549.3 2387.44   649.2 2442.52   669.2 2447.77
   709.1 2467.39   739.1 2471.19   769.1 2482.95     789 2488.56     819 2502.92
#Mann= 3 , 0 , 0
       0      .1       0   410.2    .045       0   425.2      .1       0
Bank Sta=410.2,425.2
XS Rating Curve= 0 ,0
Exp/Cntr=0.3,0.1

Type RM Length L Ch R = 1 ,2002.6  ,225,240.1,255.1
XS GIS Cut Line= 3
     1872210.384      119261.996     1872234.595      119050.747
     1871934.285      118483.456
#Sta/Elev= 30
       0 2424.63     9.7 2423.13    19.3 2418.78    96.6 2367.14   106.3 2362.84
     116 2360.98     145 2341.66   154.6 2337.48   212.6 2331.15   232.4 2324.02
   252.1 2320.15   360.8 2322.38   410.1 2320.95     420 2318.88   429.9 2314.47
   439.8 2313.28   449.6 2307.79   459.5 2305.62   469.4 2306.11   479.3 2309.72
   538.5 2340.51   558.3 2344.02     657 2381.81   666.9  2382.2   706.4 2403.36
   765.6 2441.74   785.4 2448.71     815 2465.34   824.9 2467.74   854.5 2466.78
#Mann= 3 , 0 , 0
       0      .1       0   449.6    .045       0   469.4      .1       0
Bank Sta=449.6,469.4
XS Rating Curve= 0 ,0
Exp/Cntr=0.3,0.1

Type RM Length L Ch R = 1 ,1762.5  ,190.6,197.2,203.8
XS GIS Cut Line= 2
     1872286.373      119136.139      1872395.08      118511.363
#Sta/Elev= 30
       0 2357.48    29.7 2339.83    39.6 2336.45    69.4 2334.76    79.3 2332.31
    89.2  2331.6     109 2321.08   118.9  2319.2   168.4  2319.2   208.1 2316.96
   277.4 2321.43   317.1 2321.52     327 2319.78   345.9 2308.08   356.7 2305.95
   360.9 2307.52   376.5 2312.88   386.4 2315.44   406.3 2326.58   455.8 2357.38
   465.7 2363.07   475.6 2367.34   485.5 2368.32   495.4 2373.03   515.3 2381.04
   535.1 2387.17   574.7 2397.65   584.6 2397.98   594.5 2400.78   634.2 2415.59
#Mann= 3 , 0 , 0
       0      .1       0   345.9    .045       0   360.9      .1       0
Bank Sta=345.9,360.9
XS Rating Curve= 0 ,0
Exp/Cntr=0.3,0.1

Type RM Length L Ch R = 1 ,1565.3  ,390.5,367.4,347.9
XS GIS Cut Line= 3
     1872318.322      119267.782     1872528.675       118856.22
     1872569.553       118444.54
#Sta/Elev= 30
       0 2426.74     9.8 2421.52    19.7 2420.83   108.2 2370.92   127.8 2366.27
   167.2  2345.5   186.8 2337.48   245.8 2332.85   275.4 2318.42   285.2 2315.97
   324.5 2313.92   383.5 2315.29   393.4 2313.11   411.4 2302.28   422.9 2300.38
   426.4 2301.99   442.5 2312.44   452.4 2316.67   462.2 2318.42   560.7 2321.73
   570.6 2323.49   600.1 2339.53   639.5  2367.3   649.4 2367.48   678.9 2389.62
   688.8 2394.52     738 2408.62   757.7 2411.16   836.5 2431.53   875.9 2435.01
#Mann= 3 , 0 , 0
       0      .1       0   411.4    .045       0   426.4      .1       0
Bank Sta=411.4,426.4
XS Rating Curve= 0 ,0
Exp/Cntr=0.3,0.1

Type RM Length L Ch R = 1 ,1197.8  ,408.3,401.5,390.8
XS GIS Cut Line= 3
     1873053.084        119178.5     1872839.819      118834.943
      1872673.03      118429.308
#Sta/Elev= 30
       0 2491.93    19.7 2479.72    98.6 2441.84   108.5 2438.22   128.2 2434.99
   138.1 2430.14   157.8 2417.52   226.8 2381.89   236.7 2377.56   246.6 2375.86
   325.5 2331.26   364.9 2323.09   394.5 2295.14   396.9 2294.25   404.4 2291.46
   411.9 2292.57   424.3 2299.76   434.3 2309.76   444.2 2316.45   454.2 2319.91
   603.7 2322.03   613.7 2328.26   663.5  2378.9   673.5 2387.24   683.5  2391.5
   693.4 2392.71   743.3 2407.77   753.2 2409.34   773.2 2407.33     843 2407.33
#Mann= 3 , 0 , 0
       0      .1       0   396.9    .045       0   411.9      .1       0
Bank Sta=396.9,411.9
XS Rating Curve= 0 ,0
Exp/Cntr=0.3,0.1

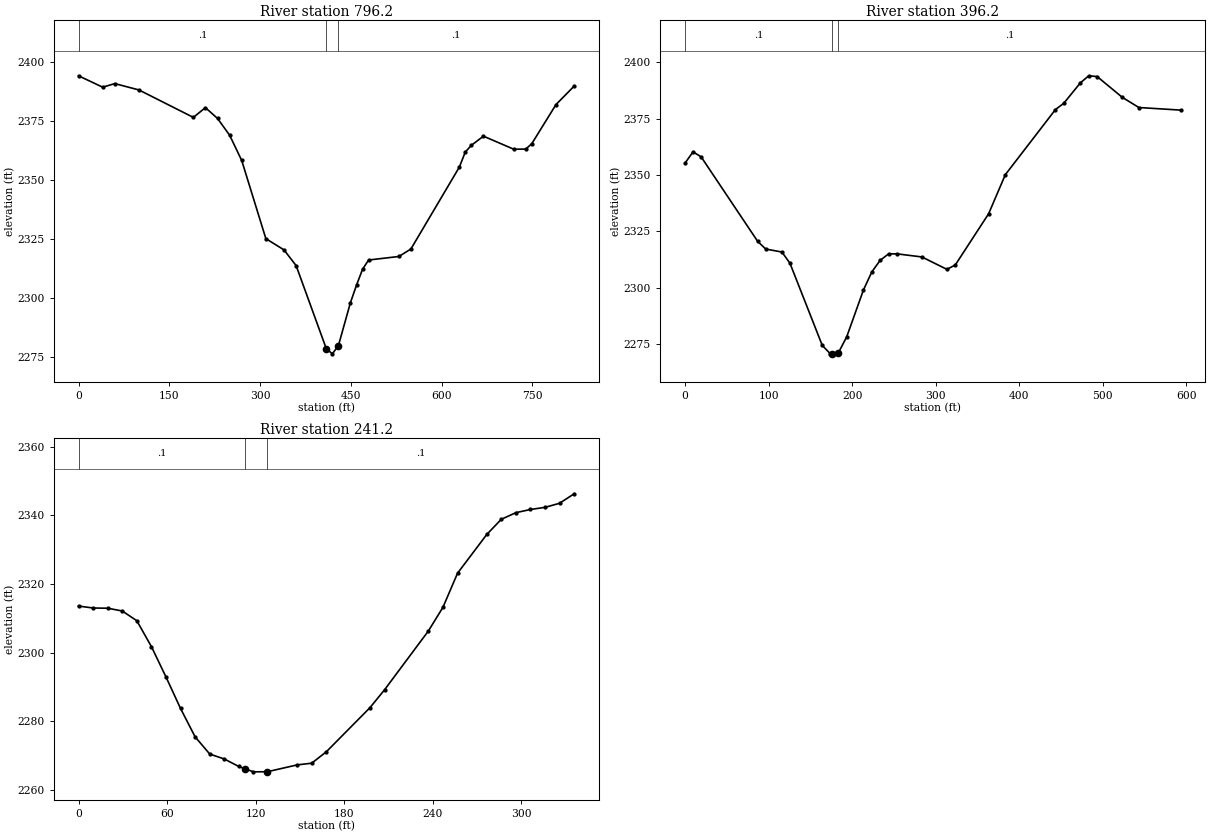
Type RM Length L Ch R = 1 ,796.2   ,405.6,400,394.9
XS GIS Cut Line= 3
     1873435.251      118826.162     1873125.998      118557.754
     1872812.321      118294.407
#Sta/Elev= 30
       0 2394.18      40 2389.34    59.9 2390.87    99.9 2388.18   189.8 2376.56
   209.7  2380.7   229.7 2376.13   249.7 2369.03   269.7 2358.33   309.6 2325.24
   339.6 2320.47   359.6 2313.83   409.5 2278.63   419.5 2276.47   429.5 2279.96
   449.4 2298.16   459.4 2305.54   469.4 2312.27   479.4 2316.19   529.4 2317.68
   549.3 2320.85   629.3  2355.5   639.2  2361.9   649.2 2364.75   669.2 2368.61
   719.2  2363.1   739.1 2363.14   749.1 2365.45   789.1    2382   819.1 2389.82
#Mann= 3 , 0 , 0
       0      .1       0   409.5    .045       0   429.5      .1       0
Bank Sta=409.5,429.5
XS Rating Curve= 0 ,0
Exp/Cntr=0.3,0.1

Type RM Length L Ch R = 1 ,396.2   ,157.5,155,152.1
XS GIS Cut Line= 3
     1873516.188      118310.398     1873351.974      118228.231
     1872987.799      118040.831
#Sta/Elev= 30
       0 2355.31     9.7  2360.3    19.3 2358.11      87 2320.62    96.6 2317.22
     116 2315.89   125.6 2310.95   164.3  2274.5     174 2270.75   176.1 2270.85
   183.6  2271.2   193.6 2278.33   213.6 2299.07   223.6 2307.06   233.6 2312.22
   243.6 2315.03   253.6 2315.09   283.5 2313.71   313.5 2308.21   323.5 2310.15
   363.4 2332.86   383.4 2350.19   443.4 2379.07   453.3 2381.82   473.3 2390.94
   483.3 2394.04   493.3 2393.69   523.3  2384.5   543.2 2379.97   593.2 2378.82
#Mann= 3 , 0 , 0
       0      .1       0   176.1    .045       0   183.6      .1       0
Bank Sta=176.1,183.6
XS Rating Curve= 0 ,0
Exp/Cntr=0.3,0.1

Type RM Length L Ch R = 1 ,241.2   ,252.1,241.2,230.5
XS GIS Cut Line= 2
     1873500.168      118122.164     1873182.821      118012.314
#Sta/Elev= 30
       0 2313.59     9.9 2313.03    19.8 2312.96    29.6 2312.16    39.5 2309.32
    49.4 2301.76    59.3 2292.89    69.1 2283.75      79 2275.46    88.9 2270.45
    98.8    2269   108.6 2266.82   112.9 2266.14   118.5 2265.26   127.9 2265.29
   148.2 2267.29     158 2267.78   167.9 2271.11   197.5 2283.99   207.4 2289.22
     237 2306.31   246.9 2313.23   256.8 2323.18   276.6 2334.47   286.4 2338.88
   296.3 2340.82   306.2 2341.75   316.1 2342.38   325.9 2343.56   335.8 2346.33
#Mann= 3 , 0 , 0
       0      .1       0   112.9    .045       0   127.9      .1       0
Bank Sta=112.9,127.9
XS Rating Curve= 0 ,0
Exp/Cntr=0.3,0.1

Chan Stop Cuts=-1
Use User Specified Reach Order=0
Composite Channel Slope=5